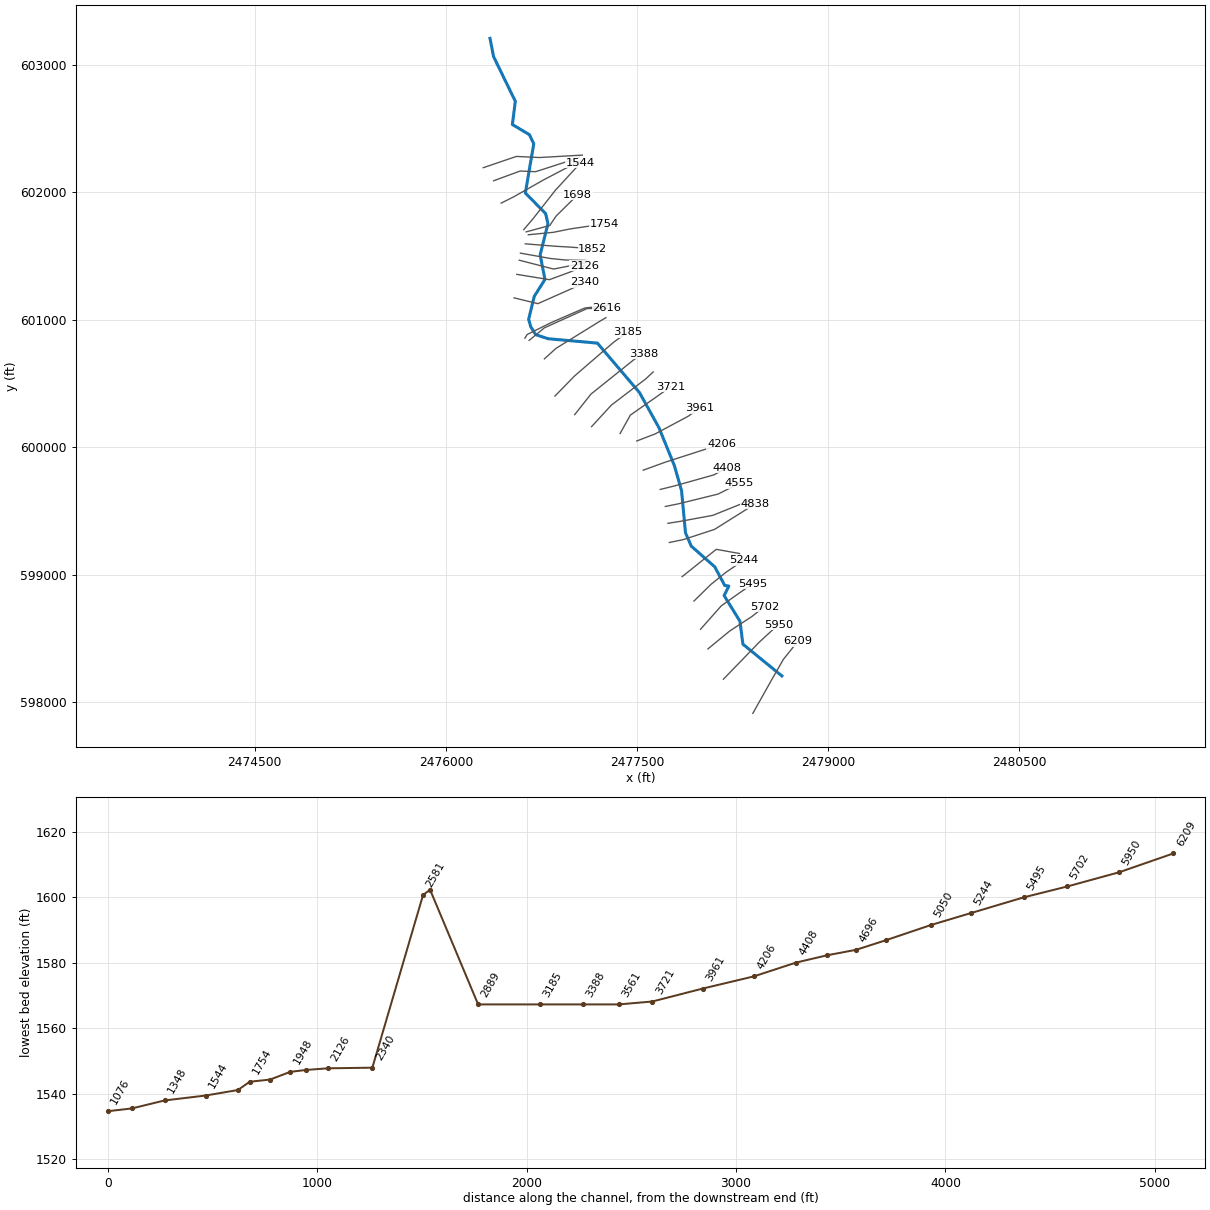
--- DETIMERRN.prj (project) ---

Proj Title=DETIMERRN
Current Plan=p01
Default Exp/Contr=0,0
English Units
Geom File=g01
Flow File=f01
Plan File=p01
BEGIN DESCRIPTION:
Stream Name:Detimer Run
Flood Zone: Zone A
Pendleton County, WV
WVDHSEM Flood Warning & Analysis Mapping
HEC-RAS Version: 5.0.7
Hydrology Method:
Regression was used
Model Notes:
Model ties in with South Fork South Branch South Potomac River
END DESCRIPTION:
DSS Export Rating Curves= 0
DSS Export Rating Curve Sorted= 0
DSS Export Volume Flow Curves= 0
DXF OffsetX= 0
DXF OffsetY= 0
DXF ScaleX= 0
DXF ScaleY= 0

--- DETIMERRN.p01 (plan) ---

Plan Title=Floodplain
Program Version=5.07
Short Identifier=Floodplain
Geom File=g01
Flow File=f01
Subcritical Flow
K Sum by GR= 0
Std Step Tol= 0.01
Critical Tol= 0.01
Num of Std Step Trials= 20
Max Error Tol= 0.3
Flow Tol Ratio= 0.001
Split Flow NTrial= 30
Split Flow Tol= 0.02
Split Flow Ratio= 0.02
Log Output Level= 0
Friction Slope Method= 1
Unsteady Friction Slope Method= 2
Unsteady Bridges Friction Slope Method= 1
Parabolic Critical Depth
Global Vel Dist= 0 , 0 , 0
Global Log Level= 0
CheckData=True
Encroach Param=-1 ,0,0, 0
Mapping Interval=1HOUR
Computation Time Step Use Courant=        0
Computation Time Step Use Time Series=    0
Computation Time Step Count To Double=0
Computation Time Step Max Doubling=0
Computation Time Step Max Halving=0
Computation Time Step Residence Courant=0
Run HTab= 0
Run UNet= 0
Run Sediment= 0
Run PostProcess= 0
Run WQNet= 0
Run RASMapper= 0
UNET Theta= 0
UNET Theta Warmup= 0
UNET ZTol= 0
UNET ZSATol= 0
UNET MxIter= 0
UNET Max Iter WO Improvement= 0
UNET MaxInSteps= 0
UNET DtIC= 0
UNET DtMin= 0
UNET MaxCRTS= 0
UNET WFStab= 0
UNET SFStab= 0
UNET WFX= 1
UNET SFX= 1
UNET 1D Methodology=Finite Difference
UNET DSS MLevel= 1
UNET Pardiso=0
UNET DZMax Abort= 0
UNET Use Existing IB Tables= 0
UNET Froude Reduction=False
UNET Froude Limit= 0
UNET Froude Power= 0
UNET D1 Cores= 0
UNET D2 Coriolis=0
UNET D2 Cores= 0
UNET D2 Theta= 1
UNET D2 Theta Warmup= 1
UNET D2 Z Tol= 0.01
UNET D2 Volume Tol= 0.01
UNET D2 Max Iterations= 20
UNET D2 Equation= 0
UNET D2 RampUpFraction=0.1
UNET D2 TimeSlices= 1
UNET D2 BCVolumeCheck=0
UNET D1D2 MaxIter= 0
UNET D1D2 ZTol=0.01
UNET D1D2 QTol=0.1
UNET D1D2 MinQTol=1
Write IC File= 0
Write IC File at Fixed DateTime=0
Write IC File at Sim End=0
Echo Input=False
Echo Parameters=False
Echo Output=False
Write Detailed= 0
HDF Write Warmup=0
HDF Write Time Slices=0
HDF Flush=0
HDF Face Node Velocities=0
HDF Compression= 1
HDF Chunk Size= 1
HDF Spatial Parts= 1
HDF Use Max Rows=0
HDF Fixed Rows= 1
Calibration Method= 0
Calibration Iterations= 20
Calibration Max Change=0.05
Calibration Tolerance=0.2
Calibration Maximum=1.5
Calibration Minimum=0.5
Calibration Optimization Method= 1
WQ AD Non Conservative
WQ ULTIMATE=-1
WQ Max Comp Step=1HOUR
WQ Output Interval=15MIN
WQ Output Selected Increments= 0
WQ Output face flow=0
WQ Output face velocity=0
WQ Output face area=0
WQ Output face dispersion=0
WQ Output cell volume=0
WQ Output cell surface area=0
WQ Output cell continuity=0
WQ Output cumulative cell continuity=0
WQ Output face conc=0
WQ Output face dconc_dx=0
WQ Output face courant=0
WQ Output face peclet=0
WQ Output face adv mass=0
WQ Output face disp mass=0
WQ Output cell mass=0
WQ Output cell source sink temp=0
WQ Output nsm pathways=0
WQ Output nsm derived pathways=0
WQ Output MaxMinRange=-1
WQ Daily Max Min Mean=-1
WQ Daily Range=0
WQ Daily Time=0
WQ Create Restart=0
WQ Fixed Restart=0
WQ System Summary=0
WQ Write To DSS=0
WQ Use Fixed Temperature=0
Sorting and Armoring Iterations= 10
XS Update Threshold= 0.02
Bed Roughness Predictor= 0
Hydraulics Update Threshold= 0.02
Energy Slope Method= 1
Volume Change Method= 1
Sediment Retention Method= 0
XS Weighting Method= 0
Number of US Weighted Cross Sections= 1
Number of DS Weighted Cross Sections= 1
Upstream XS Weight=0
Main XS Weight=1
Downstream XS Weight=0
Number of DS XS's Weighted with US Boundary= 1
Upstream Boundary Weight= 1
Weight of XSs Associated with US Boundary= 0
Number of US XS's Weighted with DS Boundary= 1
Downstream Boundary Weight= 0.5
Weight of XSs Associated with DS Boundary= 0.5
Percentile Method= 0
Sediment Output Level= 3
Mass or Volume Output= 0
Output Increment Type= 1
Profile and TS Output Increment= 1
XS Output Flag= 0
XS Output Increment= 10
Write Gradation File= 0
Read Gradation Hotstart= 0
Write HDF5 File= 1
Write Binary Output= 1
Write DSS Sediment File= 0
SV Curve= 0
Specific Gage Flag= 0

--- DETIMERRN.f01 (steady flow) ---

Flow Title=Flows
Program Version=5.07
Number of Profiles= 6
Profile Names=P100yr,P10yr,P25yr,P50yr,P500yr,P101yr
River Rch & RM=DETIMERRN,Main            ,6209
     430     202     285     356     629     524
River Rch & RM=DETIMERRN,Main            ,3961
     634     296     419     523     931     772
Boundary for River Rch & Prof#=DETIMERRN,Main            , 1
Up Type= 0
Dn Type= 3
Dn Slope=0.02588
Boundary for River Rch & Prof#=DETIMERRN,Main            , 2
Up Type= 0
Dn Type= 3
Dn Slope=0.02588
Boundary for River Rch & Prof#=DETIMERRN,Main            , 3
Up Type= 0
Dn Type= 3
Dn Slope=0.02588
Boundary for River Rch & Prof#=DETIMERRN,Main            , 4
Up Type= 0
Dn Type= 3
Dn Slope=0.02588
Boundary for River Rch & Prof#=DETIMERRN,Main            , 5
Up Type= 0
Dn Type= 3
Dn Slope=0.02588
Boundary for River Rch & Prof#=DETIMERRN,Main            , 6
Up Type= 0
Dn Type= 3
Dn Slope=0.02588
DSS Import GetInterval= 0
DSS Import GetPeak= 0
DSS Import FillOption= 0

--- DETIMERRN.g01 (geometry) ---

Geom Title=Geometry
Program Version=5.07

River Reach=DETIMERRN       ,Main
Reach XY= 30
2478636.77593247598206.5747537722478331.02325314598455.743780796
2478307.61840217598636.0988088272478183.71036765598837.105175945
2478220.20944798598911.9416224382478188.50398401598916.819386126
 2478109.6468044599063.1522967392477925.91770552599224.931459028
2477880.39191111599329.803378301     2477849.742      599659.122
     2477793.395       599856.59     2477672.572      600153.696
     2477519.613      600429.745     2477189.044      600818.037
2476802.89097008600852.4073278392476704.67471902600884.609377365
2476666.03225959600947.4033739412476649.93123483601005.367063088
 2476694.1711082601185.317018877 2476777.9265164601317.592005803
 2476740.0969735601510.939240648 2476801.2808676601755.674817046
     2476782.851      601834.688     2476623.925      601995.558
     2476690.098      602382.129     2476655.729       602453.58
     2476522.167      602533.183     2476545.331      602715.237
     2476374.416       603066.27     2476346.658      603209.281

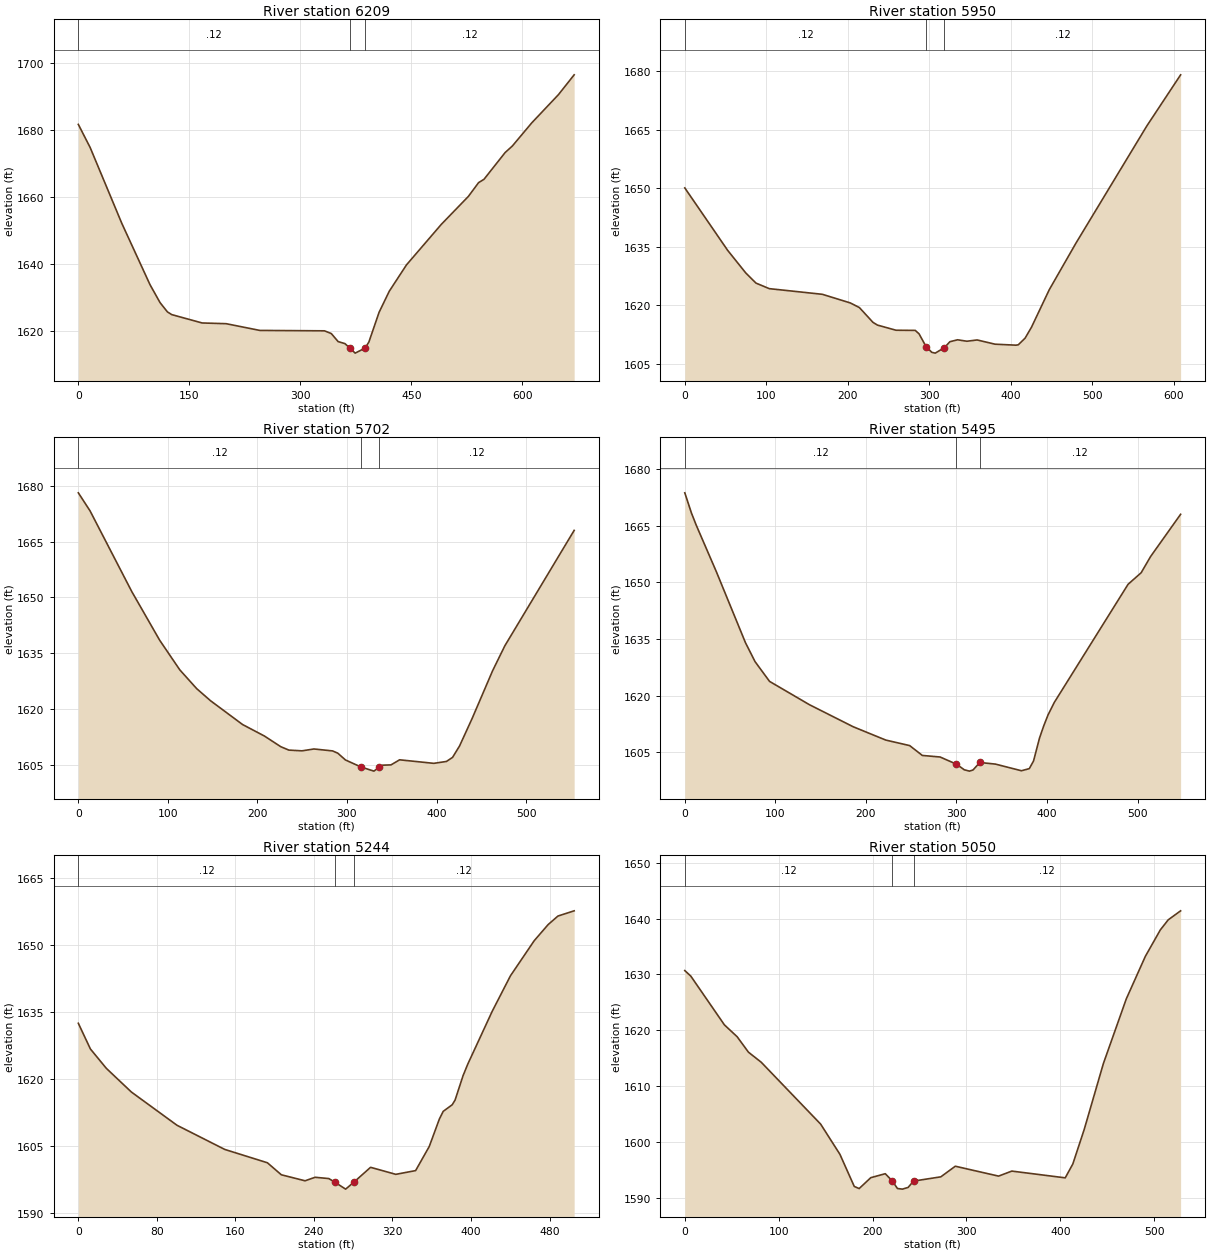
Type RM Length L Ch R = 1 ,6209    ,260.8,259.4,255.6
XS GIS Cut Line= 4
2478408.68267282597912.9761068932478557.90176223598178.772609908
2478648.83214484598337.3178924082478763.07801017598479.542337003
#Sta/Elev= 30
       0 1681.76      16 1674.85    58.7 1652.23    96.9 1633.87   110.4 1628.54
   120.4 1625.75   126.3 1624.94   167.3 1622.45   199.8 1622.23   245.3 1620.22
   332.6  1620.1   341.8 1619.29   351.1 1616.88   360.3 1616.28 367.0631614.899
   374.1 1613.44 387.5761614.957   392.6 1616.75   406.4 1625.63   420.2 1631.94
   443.4 1639.79   490.6 1651.93   527.1 1660.26   540.9 1664.38   548.1 1665.35
   576.8 1673.37   586.5 1675.31   612.7 1682.22   648.7 1690.63     670 1696.57
#Mann= 3 , 0 , 0
       0     .12       0 367.063    .045       0 387.576     .12       0
Bank Sta=367.063,387.576
XS Rating Curve= 0 ,0
Exp/Cntr(USF)=0,0
Exp/Cntr=0.3,0.1

Type RM Length L Ch R = 1 ,5950    ,248.6,248,242
XS GIS Cut Line= 4
2478177.85939389 598181.104158182478329.41003157598337.317892408
2478457.64518653598470.2161439152478609.19582422598610.109040238
#Sta/Elev= 30
       0 1650.06    52.6 1634.05    74.9 1628.23    87.4 1625.64   103.7 1624.22
   168.8 1622.77   203.1 1620.56   214.3 1619.37     231 1615.57   236.5 1614.87
   259.3 1613.55   282.9 1613.51   287.6 1612.61   296.1 1609.37   303.2 1607.88
   307.4 1607.68   318.7 1609.09   325.4 1610.61   334.8  1611.1   346.3 1610.73
   358.8 1611.06   380.9 1609.97   406.4 1609.72   409.3 1609.81   417.7 1611.52
   425.6 1614.35   447.4 1623.96     480 1635.85   567.1 1665.95   608.6 1679.07
#Mann= 3 , 0 , 0
       0     .12       0   296.1    .045       0   318.7     .12       0
Bank Sta=296.1,318.7
XS Rating Curve= 0 ,0
Exp/Cntr(USF)=0,0
Exp/Cntr=0.3,0.1

Type RM Length L Ch R = 1 ,5702    ,206.3,207.2,207.1
XS GIS Cut Line= 4
2478056.61888374 598418.92208193 2478226.8219076598558.814978253
2478401.68802801598673.0608435842478499.61305543598750.001936562
#Sta/Elev= 30
       0  1678.1    13.1 1673.25    59.7 1651.57    90.8 1638.52   113.3 1630.55
   132.2 1625.49   147.7 1622.24   183.4 1615.86   207.8 1612.77   226.1  1609.9
   235.1 1608.99   249.7 1608.79   263.2 1609.29   283.9 1608.77   289.7 1608.17
   298.3 1606.34   315.7 1604.45   330.1 1603.34   335.9 1604.39   339.7 1604.94
   349.2 1605.02   358.8 1606.38     397 1605.43   411.1 1605.94   417.9 1607.03
   425.7 1610.09   439.8  1617.5   462.6 1630.29   476.3 1637.01   553.7 1668.01
#Mann= 3 , 0 , 0
       0     .12       0   315.7    .045       0   335.9     .12       0
Bank Sta=315.7,335.9
XS Rating Curve= 0 ,0
Exp/Cntr(USF)=0,0
Exp/Cntr=0.3,0.1

Type RM Length L Ch R = 1 ,5495    ,242.1,251.2,240.1
XS GIS Cut Line= 4
2477998.33017694598572.8042678852478161.53855598598756.996581378
2478299.09990404598854.9216088042478408.68267282 598929.53115351
#Sta/Elev= 30
       0 1673.69     7.4 1668.31    12.7 1665.09    34.9 1652.78      67 1634.02
    77.6    1629    93.6 1623.78   137.8 1617.59     186 1611.77   221.9 1608.25
   248.3 1606.79   262.3 1604.18   281.9 1603.77 299.9481601.873   308.6 1600.39
   314.3 1600.03   318.3 1600.34 325.7621602.319     343 1601.89   371.7 1600.13
   380.4 1600.69   385.1 1602.72   391.7  1608.8   396.5 1612.11   401.1 1614.91
     408 1618.21   489.5 1649.49   503.9 1652.53   514.4 1656.85   547.5 1668.01
#Mann= 3 , 0 , 0
       0     .12       0 299.948    .045       0 325.762     .12       0
Bank Sta=299.948,325.762
XS Rating Curve= 0 ,0
Exp/Cntr(USF)=0,0
Exp/Cntr=0.3,0.1

Type RM Length L Ch R = 1 ,5244    ,193.3,193.7,193.4
XS GIS Cut Line= 4
2477947.03611495598794.3013537312478079.93436646598924.868056966
2478198.84332834 599020.461536122478336.40467639599113.723467002
#Sta/Elev= 30
       0 1632.49    12.3 1626.72    28.5 1622.38      54 1617.06   100.5 1609.59
   149.2 1604.16   192.6 1601.17   206.8 1598.47     231 1597.12   241.2 1597.91
   255.2 1597.62   261.8 1596.74   272.3 1595.25   280.8 1596.83   297.7 1600.15
   323.4 1598.57   343.6 1599.41   357.5 1604.83   367.8 1610.99   371.7 1612.71
   380.9  1614.2   383.8 1615.25   391.9 1620.71   396.7  1623.3   421.6 1635.17
   440.2 1643.15   464.4 1651.03   478.6 1654.65   488.6 1656.57   505.1 1657.74
#Mann= 3 , 0 , 0
       0     .12       0   261.8    .045       0   280.8     .12       0
Bank Sta=261.8,280.8
XS Rating Curve= 0 ,0
Exp/Cntr(USF)=0,0
Exp/Cntr=0.3,0.1

Type RM Length L Ch R = 1 ,5050    ,212.2,212.5,207.9
XS GIS Cut Line= 4
2477853.77418407598985.4883120392477970.35159768599078.750242922
2478121.90223536599199.9907530682478303.76300058 599167.34907726
#Sta/Elev= 30
       0 1630.68     6.4 1629.69    42.2 1620.96    55.8 1618.83    67.8 1616.07
    81.4 1614.27   144.7 1603.19   165.2 1597.79   180.5 1592.03   185.7 1591.65
   198.1  1593.6   213.5 1594.31   220.8 1593.06   226.5 1591.66   231.8 1591.55
   237.9 1591.86   243.6 1592.99   272.7 1593.75   288.1 1595.65   334.2 1593.88
   348.3 1594.78   405.2 1593.57   413.3 1596.06   425.5 1602.28   445.8 1614.02
   470.2  1625.6   490.5 1633.22   506.5 1637.97   514.9 1639.77   528.1 1641.38
#Mann= 3 , 0 , 0
       0     .12       0   220.8    .045       0   243.6     .12       0
Bank Sta=220.8,243.6
XS Rating Curve= 0 ,0
Exp/Cntr(USF)=0,0
Exp/Cntr=0.3,0.1

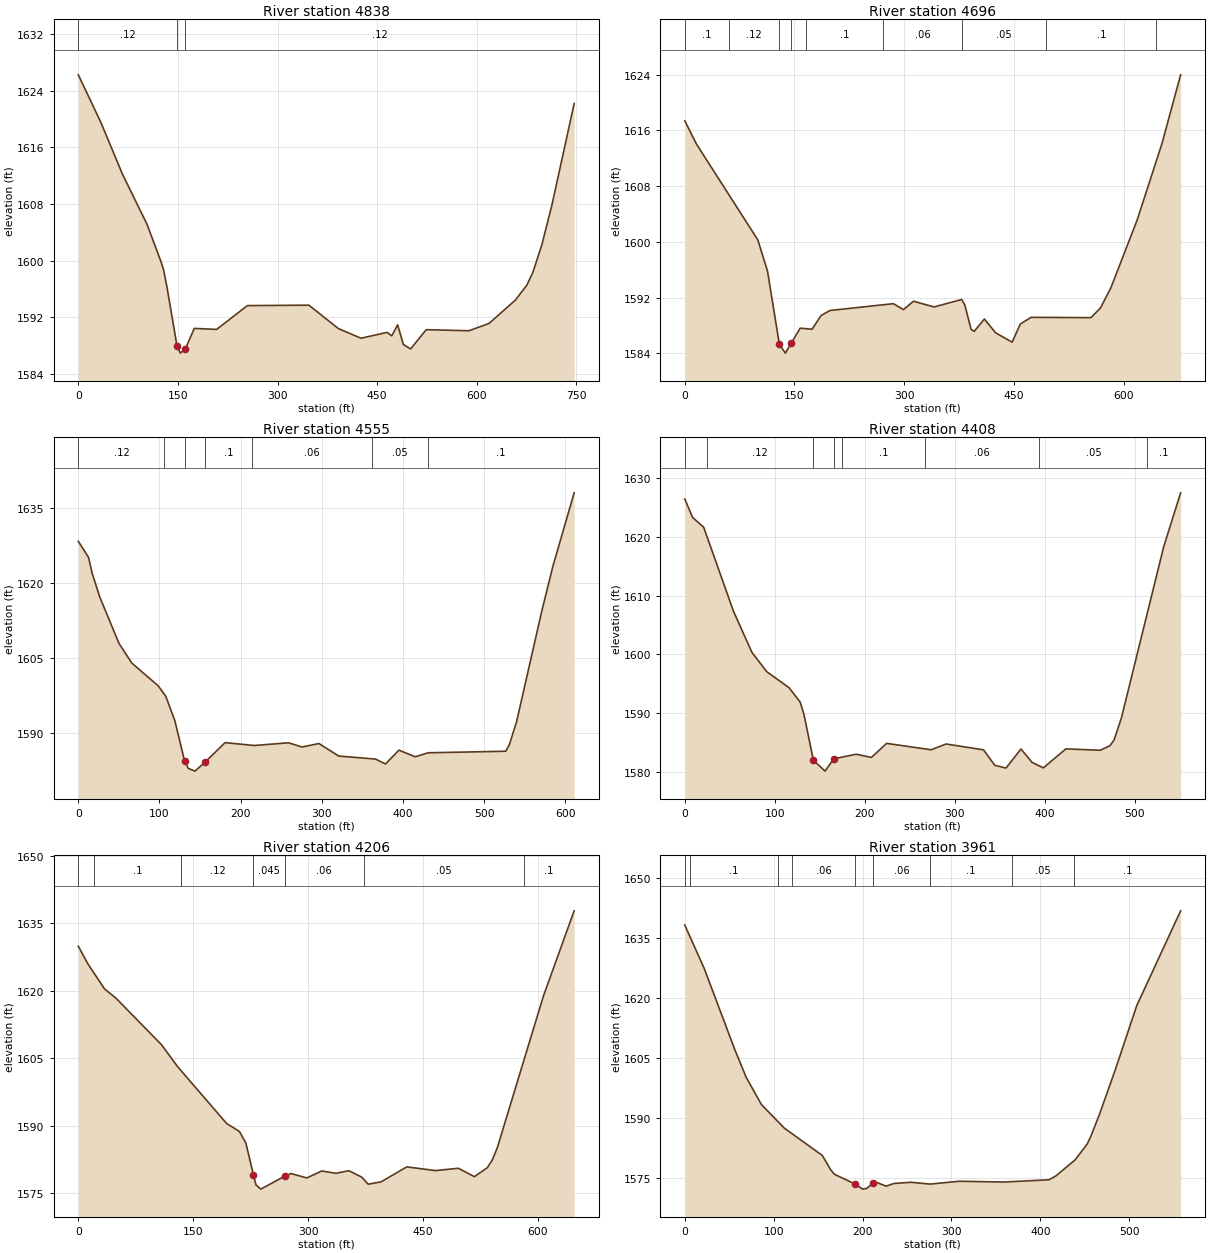
Type RM Length L Ch R = 1 ,4838    ,142.2,142.4,140.5
XS GIS Cut Line= 4
2477753.51760837599253.6163633262477865.43192543599276.931846046
2478107.91294573599356.204487296  2478427.335059599556.717638693
#Sta/Elev= 30
       0 1626.25    33.9 1619.54    66.6  1612.2   103.4 1605.16   124.1 1599.97
   128.3 1598.75   133.5 1596.28   148.6 1587.96   153.6 1586.96   161.3 1587.58
   174.6 1590.45   208.3 1590.31   254.6 1593.67   347.2 1593.73   391.7 1590.42
   425.7 1589.06   464.8 1589.89     472  1589.4   480.8 1590.95   489.5 1588.18
   500.3 1587.55   523.9 1590.27   588.1 1590.12   618.4 1591.15   657.8 1594.42
   675.2 1596.53   684.5 1598.37     698 1602.27   712.9 1607.78   746.6 1622.19
#Mann= 3 , 0 , 0
       0     .12       0   148.6    .045       0   161.3     .12       0
Bank Sta=148.6,161.3
XS Rating Curve= 0 ,0
Exp/Cntr(USF)=0,0
Exp/Cntr=0.3,0.1

Type RM Length L Ch R = 1 ,4696    ,140,140.8,142.2
XS GIS Cut Line= 4
2477743.10647511599404.2944215242477842.06480843599419.919421524
2478095.53703064599466.7944215242478392.41203067599586.586088195
#Sta/Elev= 30
       0 1617.38    15.9 1614.05    99.9 1600.28   113.1 1595.81   129.4 1585.28
   137.5 1584.03   145.6 1585.46   157.8 1587.61   174.1 1587.46   186.3 1589.42
   198.5 1590.15   285.3 1591.13     299 1590.27   312.7 1591.48   340.9 1590.66
   378.7 1591.73     383 1590.93   391.6 1587.43   395.9 1587.16   409.7 1588.93
     425 1586.95   447.7  1585.6   458.8  1588.2   473.6 1589.17   555.5 1589.12
   568.5 1590.52   582.7  1593.4   618.6 1603.12   652.5 1614.08   678.1 1623.98
#Mann= 9 ,-1 , 0
       0      .1       0    60.6     .12       0   129.4    .045       0
   145.6     .12       0  165.72      .1       0  271.21     .06       0
  378.57     .05       0  494.66      .1       0  644.82     .12       0
Bank Sta=129.4,145.6
XS Rating Curve= 0 ,0
Exp/Cntr(USF)=0,0
Exp/Cntr=0.3,0.1

Type RM Length L Ch R = 1 ,4555    ,145.8,146.5,146.2
XS GIS Cut Line= 4
2477722.27314177599536.2388659722477824.70369732599557.072199315
2478135.46758622599633.4610881952478302.13425288599716.794421539
#Sta/Elev= 30
       0 1628.31    12.7 1625.06    16.8 1622.04    26.4 1617.17    50.1 1607.88
    65.8 1603.96    98.4 1599.39   107.7 1597.32     119 1592.38   130.9 1584.35
   135.5 1582.86   143.7 1582.32   156.1 1584.11   180.8 1588.02   216.8 1587.45
     259 1587.99   275.5 1587.15   296.5 1587.84   320.8 1585.34   366.1 1584.73
   378.5 1583.75     395 1586.52   415.2 1585.19     431 1585.99   526.6  1586.3
   531.1 1587.61     540 1592.22   570.8  1614.2   584.7 1623.31   610.9 1638.01
#Mann= 7 ,-1 , 0
       0     .12       0  106.14      .1       0   130.9    .045       0
   156.1      .1       0  214.05     .06       0  362.37     .05       0
  430.58      .1       0
Bank Sta=130.9,156.1
XS Rating Curve= 0 ,0
Exp/Cntr(USF)=0,0
Exp/Cntr=0.3,0.1

Type RM Length L Ch R = 1 ,4408    ,201.7,202.4,204.1
XS GIS Cut Line= 4
2477682.34258619599669.9194215392477795.18980843  599697.6971993
2478104.21758622599784.5027548822478203.17591956599840.058310419
#Sta/Elev= 30
       0 1626.49     8.7 1623.35      21 1621.68      54 1607.39    74.6 1600.35
      91 1597.07   115.8 1594.34   128.2 1591.87   132.4 1589.76   142.8 1581.99
   155.7 1580.12   165.6 1582.22   190.5    1583   207.2 1582.45   224.2 1584.85
   273.6 1583.76   290.3 1584.74   331.8 1583.75   344.3 1581.11   356.7 1580.64
   373.4 1583.89   385.8 1581.59   398.3 1580.68   423.2 1583.91   461.4 1583.68
   472.2 1584.45   476.8 1585.44   484.9 1589.16   531.8  1618.3   550.7 1627.55
#Mann= 8 ,-1 , 0
       0      .1       0   24.86     .12       0   142.8    .045       0
   165.6     .12       0  174.78      .1       0  266.45     .06       0
  393.77     .05       0  513.79      .1       0
Bank Sta=142.8,165.6
XS Rating Curve= 0 ,0
Exp/Cntr(USF)=0,0
Exp/Cntr=0.3,0.1

Type RM Length L Ch R = 1 ,4206    ,242.5,244.4,248.4
XS GIS Cut Line= 4
2477548.66203067 599820.961088212477720.53703067 599883.46108821
2478086.85647511600001.5166437482478163.24536398600024.086088195
#Sta/Elev= 30
       0 1629.91    12.5 1625.98    34.3  1620.4      49 1618.38   108.6 1608.01
   129.9 1603.07   193.6 1590.49   210.4  1588.7   218.8 1586.11   228.7 1579.04
   231.9 1576.85   238.2 1575.89   269.3 1578.75   277.7 1579.35   298.4 1578.38
   317.7 1579.92   336.5 1579.41   353.3 1579.99   370.1 1578.55   378.5 1576.99
   395.3 1577.51   428.9 1580.84   466.2 1580.01   496.2 1580.53   517.2 1578.66
     534 1580.66   540.2 1582.28   546.9 1585.01   607.4  1618.9   647.4 1637.78
#Mann= 7 ,-1 , 0
       0     .12       0   20.91      .1       0  134.67     .12       0
   228.7    .045       0   269.3     .06       0  372.79     .05       0
   581.6      .1       0
Bank Sta=228.7,269.3
XS Rating Curve= 0 ,0
Exp/Cntr(USF)=0,0
Exp/Cntr=0.3,0.1

Type RM Length L Ch R = 1 ,3961    ,258.9,239.9,255.5
XS GIS Cut Line= 4
 2477498.3148084600050.1277548822477642.41203067600105.683310419
2477899.35647509600242.8360881952477991.37036398  600307.0721993
#Sta/Elev= 30
       0 1638.16    21.9 1627.28    56.2 1607.08      69 1600.14    86.2 1593.31
   111.9 1587.43   154.8 1580.57   163.9 1577.09   168.4 1575.88     191 1573.51
     191  1573.5   200.2 1572.17   204.7 1572.36   211.7 1573.64   216.5 1573.79
   226.5 1572.92   235.4 1573.58   254.6 1573.88   275.9 1573.43     309 1574.14
   358.9 1573.94   409.8  1574.5   417.8 1575.51   439.4 1579.53   452.8 1583.45
   456.8 1585.32   466.8 1590.98     484 1601.75   508.5    1618   557.9 1641.71
#Mann= 9 ,-1 , 0
       0      .1       0    6.15      .1       0  104.75     .12       0
  121.17     .06       0     191    .045       0   211.7     .06       0
  275.56      .1       0  368.04     .05       0  437.92      .1       0
Bank Sta=191,211.7
XS Rating Curve= 0 ,0
Exp/Cntr(USF)=0,0
Exp/Cntr=0.3,0.1

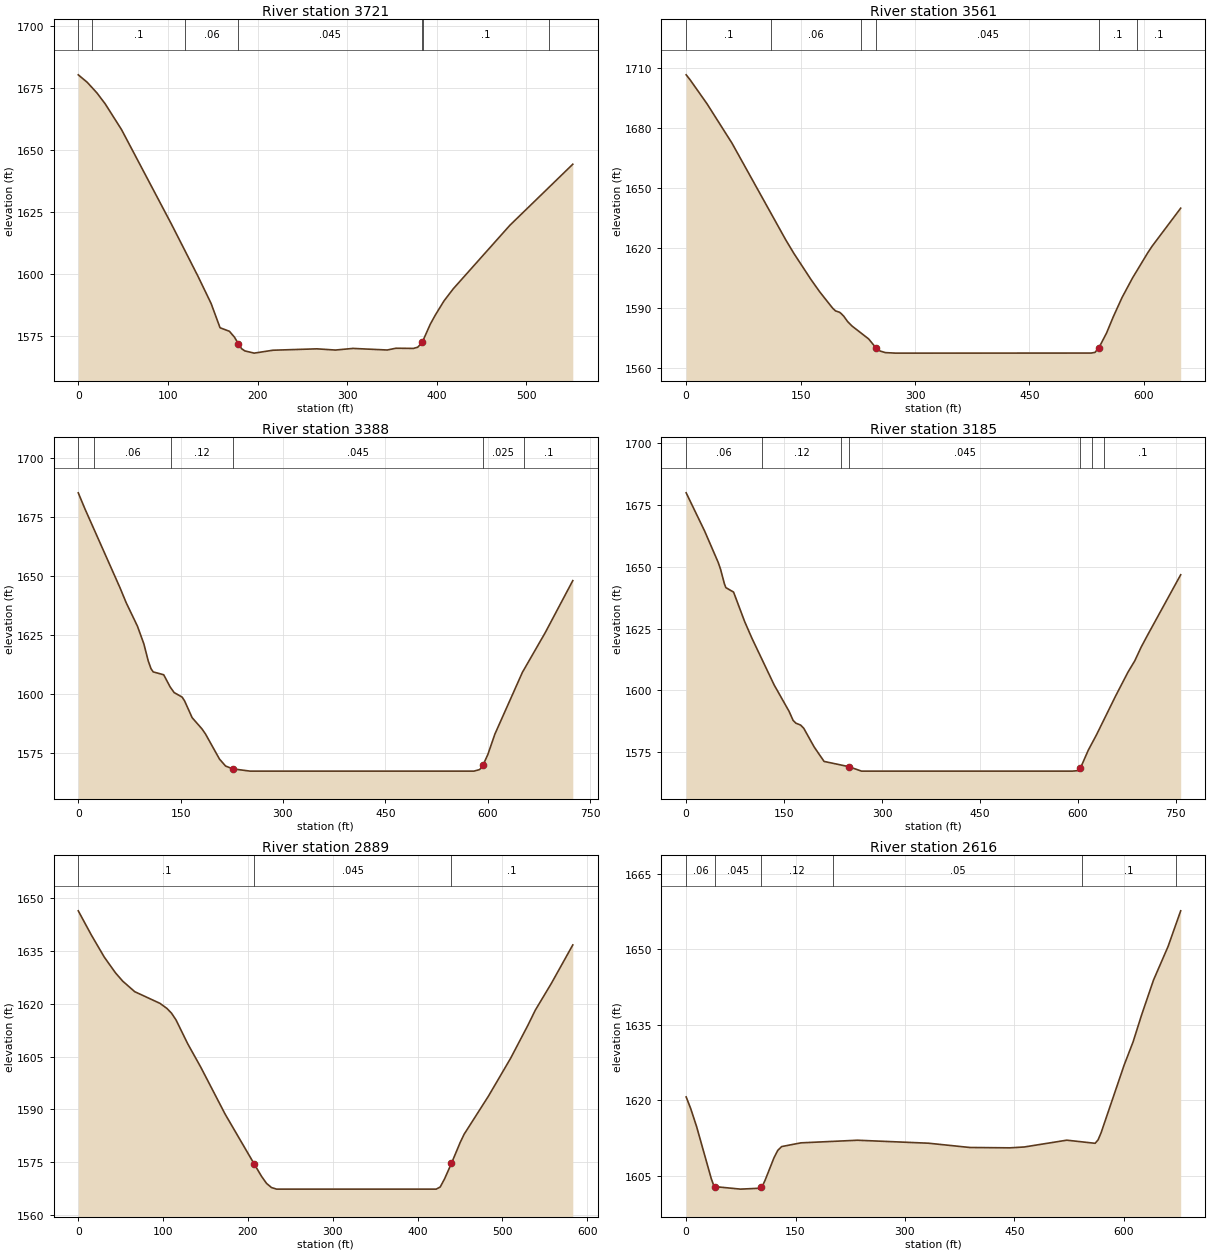
Type RM Length L Ch R = 1 ,3721    ,166.7,160.3,163.4
XS GIS Cut Line= 4
2477367.32588897600108.7248242242477447.96758622600253.252754867
2477656.30091953600399.086088195 2477763.9398084600475.474977106
#Sta/Elev= 30
       0 1680.49      10 1677.47    20.8  1673.2      30 1668.81    48.3 1658.38
   104.1 1620.17   133.5 1599.29   148.2 1588.28   158.2 1578.47   168.7 1577.03
   174.4 1574.62 178.6591571.945   182.3 1570.01   185.9 1569.12   196.3 1568.23
   217.2  1569.4   266.3 1569.96   286.9 1569.47   306.5 1570.13   344.7 1569.49
   354.4  1570.2     374 1570.13   378.8 1570.62 383.7291572.525   392.7 1579.84
   398.4 1583.59   408.1  1589.3   418.5 1594.21   481.6  1619.8   551.8 1644.43
#Mann= 7 ,-1 , 0
       0      .1       0   15.39      .1       0   119.4     .06       0
 178.659    .045       0 383.729    .025       0  384.79      .1       0
  524.95      .1       0
Bank Sta=178.659,383.729
XS Rating Curve= 0 ,0
Exp/Cntr(USF)=0,0
Exp/Cntr=0.3,0.1

Type RM Length L Ch R = 1 ,3561    ,182.2,173.2,175.1
XS GIS Cut Line= 4
2477143.71743334600162.7447844892477298.66203064600331.377754882
2477569.49536395600537.9749771062477626.78703067600591.794421539
#Sta/Elev= 30
       0 1706.41     5.1 1703.97    27.4  1691.9      60 1672.31   130.6 1623.91
   141.4 1617.06   163.6 1604.14   174.9 1598.06   191.9 1589.86   195.8 1588.45
   201.2 1587.74   203.2 1587.11   206.6 1585.79   211.7 1583.09   217.4 1580.89
   239.2 1574.45 249.2371569.779   254.4 1568.37   261.2  1567.6   274.4 1567.34
     531 1567.37     536 1567.73 541.0311569.981   551.1 1577.38   559.8 1585.39
   571.4 1595.11   585.3 1604.99   605.1 1617.47   610.8 1620.75   648.3 1639.78
#Mann= 6 ,-1 , 0
       0      .1       0  111.72     .06       0  229.02    .055       0
 249.237    .045       0 541.031      .1       0  591.17      .1       0
Bank Sta=249.237,541.031
XS Rating Curve= 0 ,0
Exp/Cntr(USF)=0,0
Exp/Cntr=0.3,0.1

Type RM Length L Ch R = 1 ,3388    ,192.5,202.8,206.2
XS GIS Cut Line= 4
2477011.06913366600256.7976081182477138.93980843600418.183310434
2477479.21758622600690.7527548672477548.66203067600735.891643763
#Sta/Elev= 30
       0 1685.32     9.8 1678.51    61.1 1645.11    70.3 1638.69    86.7 1628.81
    96.1 1621.31   102.5  1614.1   106.6 1610.77   109.8 1609.41   125.2 1608.19
   134.7 1603.01   140.5 1600.65   152.2 1598.72   155.8 1597.12   166.9 1589.99
   181.3 1585.23   186.4 1583.11     207 1572.43   215.9  1569.5  226.23 1568.31
   251.8 1567.34   579.8 1567.34   587.6 1567.95     590 1568.48 593.2751569.978
   600.3 1574.45   610.5 1583.01   650.9 1609.25   684.3 1626.04   724.7  1648.1
#Mann= 6 ,-1 , 0
       0      .1       0   23.34     .06       0  135.48     .12       0
  226.23    .045       0 593.275    .025       0  652.85      .1       0
Bank Sta=226.23,593.275
XS Rating Curve= 0 ,0
Exp/Cntr(USF)=0,0
Exp/Cntr=0.3,0.1

Type RM Length L Ch R = 1 ,3185    ,261.3,295.7,213.6
XS GIS Cut Line= 4
  2476856.303575 600402.656518412477010.46758622600560.544421524
2477316.02314174600824.4333104192477423.66203067600902.558310434
#Sta/Elev= 30
       0    1680    28.3 1664.52    49.3 1651.68    52.8 1648.95    58.5 1643.24
    60.8 1641.62    72.6 1639.82    89.6 1627.87   100.8 1621.09   134.8 1602.21
   157.5  1591.6   163.8 1587.88     168 1586.76   175.3 1585.98   180.1 1584.69
     196 1577.14   211.2 1571.27 248.7391569.167   268.6 1567.34   591.2 1567.34
   599.7 1567.52 603.6851568.454   615.9 1575.83   628.6 1582.12   657.4 1597.59
   676.8 1607.48   687.1 1612.01   696.8 1617.51   706.8 1622.46   757.4 1646.83
#Mann= 7 ,-1 , 0
       0     .06       0  116.66     .12       0  237.52    .025       0
 248.739    .045       0 603.685    .025       0   621.5      .1       0
  640.33      .1       0
Bank Sta=248.739,603.685
XS Rating Curve= 0 ,0
Exp/Cntr(USF)=0,0
Exp/Cntr=0.3,0.1

Type RM Length L Ch R = 1 ,2889    ,219.6,229.5,385.5
XS GIS Cut Line= 4
2476773.26301017600694.3289201682476864.63454669600776.960570587
2477210.25731527600990.6905125392477256.34035108601017.704705945
#Sta/Elev= 30
       0 1646.42    15.6 1639.47    30.7 1633.26    43.9 1628.79    52.4 1626.44
    66.6 1623.44    96.3 1620.13   104.5 1618.69   109.9 1617.35   115.3  1615.4
     129 1608.66   144.5 1601.96     173 1588.71   207.5 1574.45   216.2 1570.92
     222 1568.96   227.8 1567.79   233.8 1567.34     422 1567.34   426.7 1567.95
   431.9 1570.29     440 1574.69   450.2 1580.58   454.9 1582.94   483.6 1593.78
   509.7 1604.52   530.1 1613.91   538.8 1618.19   557.9 1625.87     583 1636.73
#Mann= 3 , 0 , 0
       0      .1       0   207.5    .045       0     440      .1       0
Bank Sta=207.5,440
XS Rating Curve= 0 ,0
Exp/Cntr(USF)=0,0
Exp/Cntr=0.5,0.3

Type RM Length L Ch R = 1 ,2616    ,39.4,33.5,25.1
XS GIS Cut Line= 4
 2476653.8523303600839.4698679292476772.99991354600937.686118983
2477107.90122861601089.0357517562477264.08116882601092.255956709
#Sta/Elev= 30
       0 1620.67     6.3 1618.33    14.4 1614.74    34.3 1604.51    37.4 1603.24
      40 1602.85    74.6 1602.36    99.7 1602.53   102.5 1602.78   105.4 1603.24
   108.2 1604.11   120.4 1608.58   125.6 1610.05   130.9 1610.81   157.3 1611.55
     235 1612.07   332.2 1611.48     389 1610.63   443.8 1610.56   463.6 1610.73
   521.9 1612.08   560.8 1611.46   564.8 1612.14   568.8 1613.49   600.5 1626.97
   612.8 1631.59   624.5 1636.95   640.8 1643.87   660.8 1650.55   678.1 1657.63
#Mann= 6 ,-1 , 0
       0     .06       0      40    .045       0   102.5     .12       0
  201.02     .05       0  542.68      .1       0  671.16      .1       0
Bank Sta=40,102.5
XS Rating Curve= 0 ,0
Exp/Cntr(USF)=0,0
Exp/Cntr=0.3,0.1

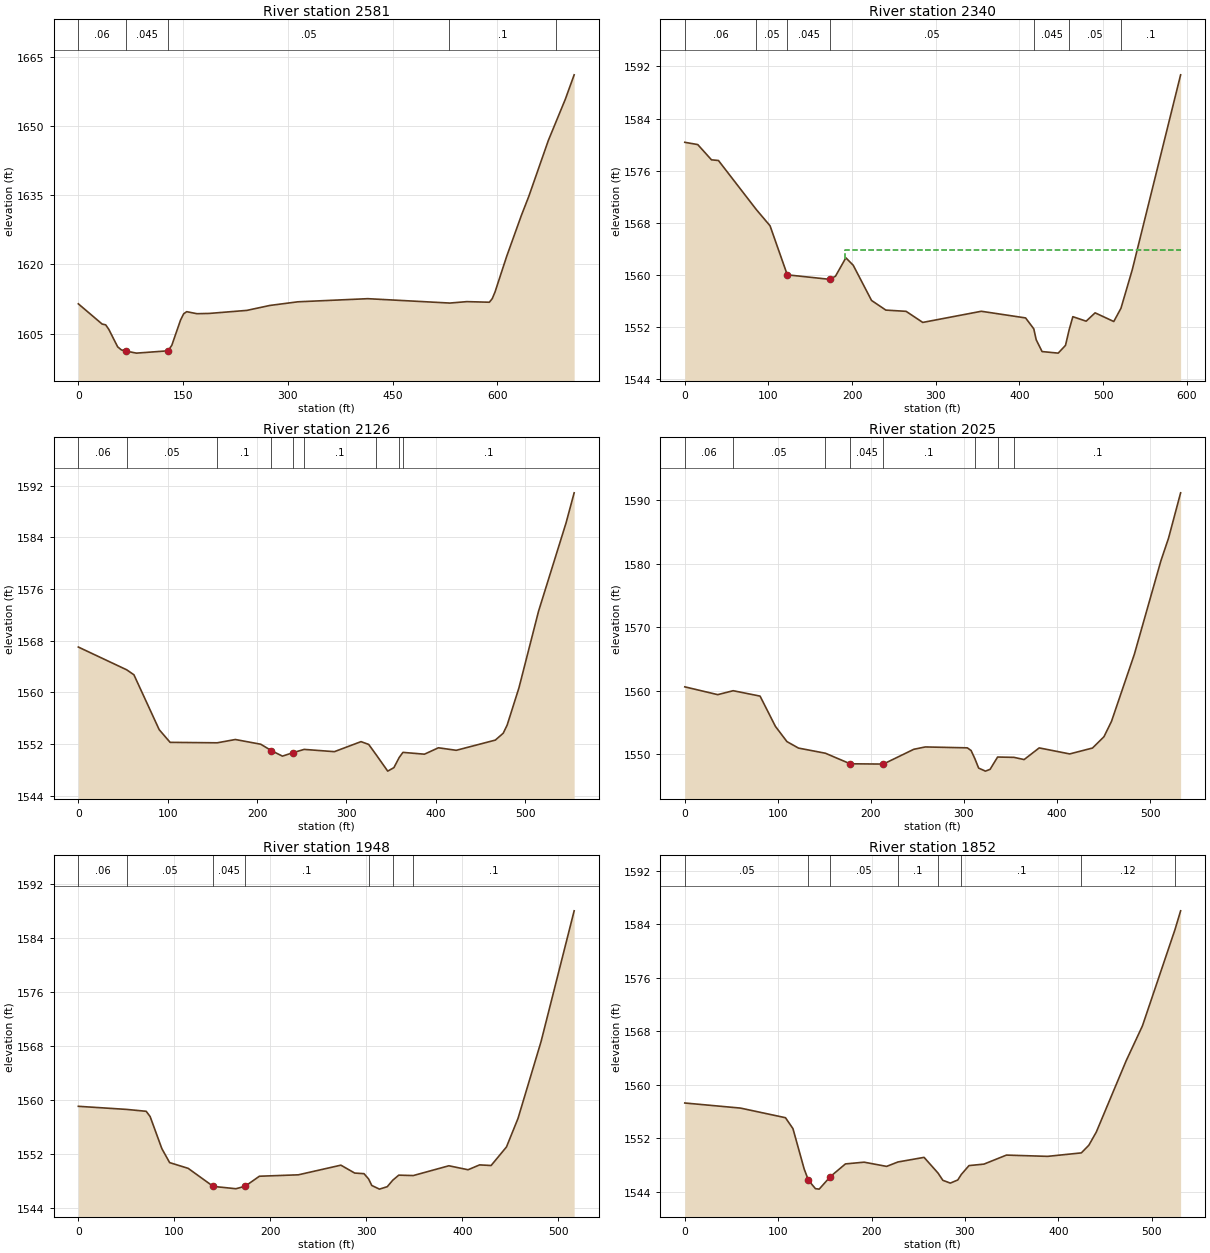
Type RM Length L Ch R = 1 ,2581    ,258.1,242.1,218.9
XS GIS Cut Line= 6
2476620.74074121600856.3477416052476627.53501514600868.635108615
 2476638.1886148600885.5911663032476826.43980843600978.947199315
2477090.32869732601093.5305326582477267.41203064601112.627754867
#Sta/Elev= 30
       0 1611.44    34.1 1607.05    39.2 1606.88    43.6 1605.91    56.3 1602.11
    61.5 1601.45    68.3 1601.19    83.2 1600.74   128.4 1601.24   133.9 1602.46
   146.3 1607.89   150.8 1609.27   155.2 1609.74   169.8  1609.3   187.7 1609.36
   241.4 1610.02   274.2 1611.09   314.3 1611.88   414.5 1612.56   531.9 1611.61
   556.4 1611.92   588.6 1611.79   592.7 1612.57   596.7 1614.02   613.4 1621.76
   634.5 1630.67     645 1634.75   673.1 1646.94   697.3 1655.84     710 1661.16
#Mann= 5 ,-1 , 0
       0     .06       0    68.3    .045       0   128.4     .05       0
  530.81      .1       0  684.09      .1       0
Bank Sta=68.3,128.4
XS Rating Curve= 0 ,0
Exp/Cntr(USF)=0,0
Exp/Cntr=0.3,0.1

Type RM Length L Ch R = 1 ,2340    ,219.2,214,213.7
XS GIS Cut Line= 4
2476535.71302137601173.0975090382476722.25665083  601127.6697858
2476977.42513881601240.7558202432477086.64498404601293.915921904
#Sta/Elev= 30
       0 1580.37    15.5 1580.02    31.9 1577.68    40.2 1577.58    85.5 1570.05
   101.9 1567.56   122.5 1560.04   173.21559.349   180.1 1559.83   192.5 1562.65
   201.3 1561.51   223.2 1556.11   240.3 1554.63   264.5 1554.44   284.4 1552.74
   354.4 1554.45   407.3 1553.43   417.1 1551.76     420 1550.08     427 1548.27
   446.3 1548.03     455 1549.22   459.4 1551.63   463.8 1553.62   479.7 1552.93
   490.4 1554.21   512.7 1552.88   521.3 1554.91   534.8 1560.82   592.6 1590.72
#Mann= 7 ,-1 , 0
       0     .06       0    85.5     .05       0   122.5    .045       0
   173.2     .05       0   417.1    .045       0   459.4     .05       0
   521.3      .1       0
#XS Ineff= 2 , 0
                          191.63         1563.82
Permanent Ineff=
       F       F
Bank Sta=122.5,173.2
XS Rating Curve= 0 ,0
Exp/Cntr(USF)=0,0
Exp/Cntr=0.3,0.1

Type RM Length L Ch R = 1 ,2126    ,104.5,100.8,97.6
XS GIS Cut Line= 4
2476557.34258622601357.4194215242476812.55091956601315.752754882
2476977.48147509601376.5166437632477086.85647511601426.863865986
#Sta/Elev= 30
       0 1567.02    54.1  1563.5    62.2 1562.73    90.5 1554.24   102.7 1552.28
   155.4 1552.21   175.7 1552.72   204.1 1551.99     216    1551   228.4 1550.15
   240.3 1550.69   252.7 1551.19   286.5 1550.84   316.3 1552.39   324.9 1551.96
  333.07  1550.4   346.2 1547.83   353.1 1548.37     359 1549.93   363.2 1550.73
   387.3 1550.45   402.9 1551.44   422.9 1551.05   466.6 1552.63   475.4 1553.69
   479.8 1554.94     493  1560.7     515 1572.58   545.7  1586.2   554.8 1590.87
#Mann= 9 ,-1 , 0
       0     .06       0    54.1     .05       0   155.4      .1       0
     216    .045       0   240.3      .1       0   252.7      .1       0
  333.07    .045       0     359      .1       0   363.2      .1       0
Bank Sta=216,240.3
XS Rating Curve= 0 ,0
Exp/Cntr(USF)=0,0
Exp/Cntr=0.3,0.1

Type RM Length L Ch R = 1 ,2025    ,79.3,77.5,82.8
XS GIS Cut Line= 4
 2476576.4398084601468.5305326432476845.53703067 601399.08608821
2476934.07869729601416.4471993152477095.53703064601449.433310434
#Sta/Elev= 30
       0 1560.62    35.4 1559.39      52 1560.01    80.9 1559.16    97.4 1554.39
   109.8 1551.99   122.2 1550.97   151.1 1550.16  177.711548.498   213.4 1548.45
   246.1 1550.78   258.5 1551.15   303.6 1551.01   307.7 1550.59   311.8 1549.29
   315.8 1547.82   323.1 1547.34   328.1 1547.62   336.2 1549.56   353.8 1549.51
   364.7 1549.16   380.9    1551   413.7 1550.05   438.2 1550.98   450.5 1552.76
   458.6 1555.18   483.1 1565.72   511.7 1580.48   519.9 1584.04   532.9 1591.19
#Mann= 8 ,-1 , 0
       0     .06       0      52     .05       0   151.1      .1       0
  177.71    .045       0   213.4      .1       0   311.8    .045       0
   336.2      .1       0   353.8      .1       0
Bank Sta=177.71,213.4
XS Rating Curve= 0 ,0
Exp/Cntr(USF)=0,0
Exp/Cntr=0.3,0.1

Type RM Length L Ch R = 1 ,1948    ,94,95.4,95.8
XS GIS Cut Line= 4
2476585.12036398 601524.086088212476817.75925285601482.419421524
 2476935.8148084601470.2666437482477097.27314174601466.794421524
#Sta/Elev= 30
       0 1559.02    50.4 1558.56    70.7 1558.28    74.8  1557.5      87 1552.75
    95.1 1550.68   114.4 1549.83  140.521547.154   164.2 1546.81   173.8 1547.18
   188.6 1548.66   229.2 1548.87   273.5  1550.3   287.9 1549.13   297.6 1549.04
   302.4 1548.25   305.7 1547.29   313.7 1546.75   321.8 1547.11   327.6 1548.08
   333.8 1548.82   348.9 1548.76     386 1550.21     406 1549.62     418 1550.34
     430 1550.25     446    1553     458 1557.22     482  1568.6   516.5 1587.98
#Mann= 7 ,-1 , 0
       0     .06       0    50.4     .05       0  140.52    .045       0
   173.8      .1       0   302.4    .045       0   327.6      .1       0
   348.9      .1       0
Bank Sta=140.52,173.8
XS Rating Curve= 0 ,0
Exp/Cntr(USF)=0,0
Exp/Cntr=0.3,0.1

Type RM Length L Ch R = 1 ,1852    ,96.5,98.2,99.6
XS GIS Cut Line= 4
 2476623.3148084601597.0027548672476861.16203064601577.905532643
2476953.17591953601572.6971993152477152.82869729601558.808310434
#Sta/Elev= 30
       0 1557.29    59.6 1556.53   107.8 1555.09   115.8 1553.46   127.8 1547.43
  132.411545.726   139.9 1544.48   143.9 1544.41   155.9 1546.29     172 1548.18
     192 1548.44   216.1 1547.81   228.2 1548.47   256.2 1549.16   271.1 1546.82
   276.3 1545.73   284.3 1545.31   292.3 1545.78   296.1 1546.61   304.3 1547.93
   320.3 1548.15   344.4  1549.5   388.5 1549.31   424.6 1549.83   432.6 1550.97
   440.6 1552.94   472.6 1563.61     490 1568.82   524.8  1583.2   530.9 1586.03
#Mann= 8 ,-1 , 0
       0     .05       0  132.41    .045       0   155.9     .05       0
   228.2      .1       0   271.1    .045       0   296.1      .1       0
   424.6     .12       0   524.8      .1       0
Bank Sta=132.41,155.9
XS Rating Curve= 0 ,0
Exp/Cntr(USF)=0,0
Exp/Cntr=0.3,0.1

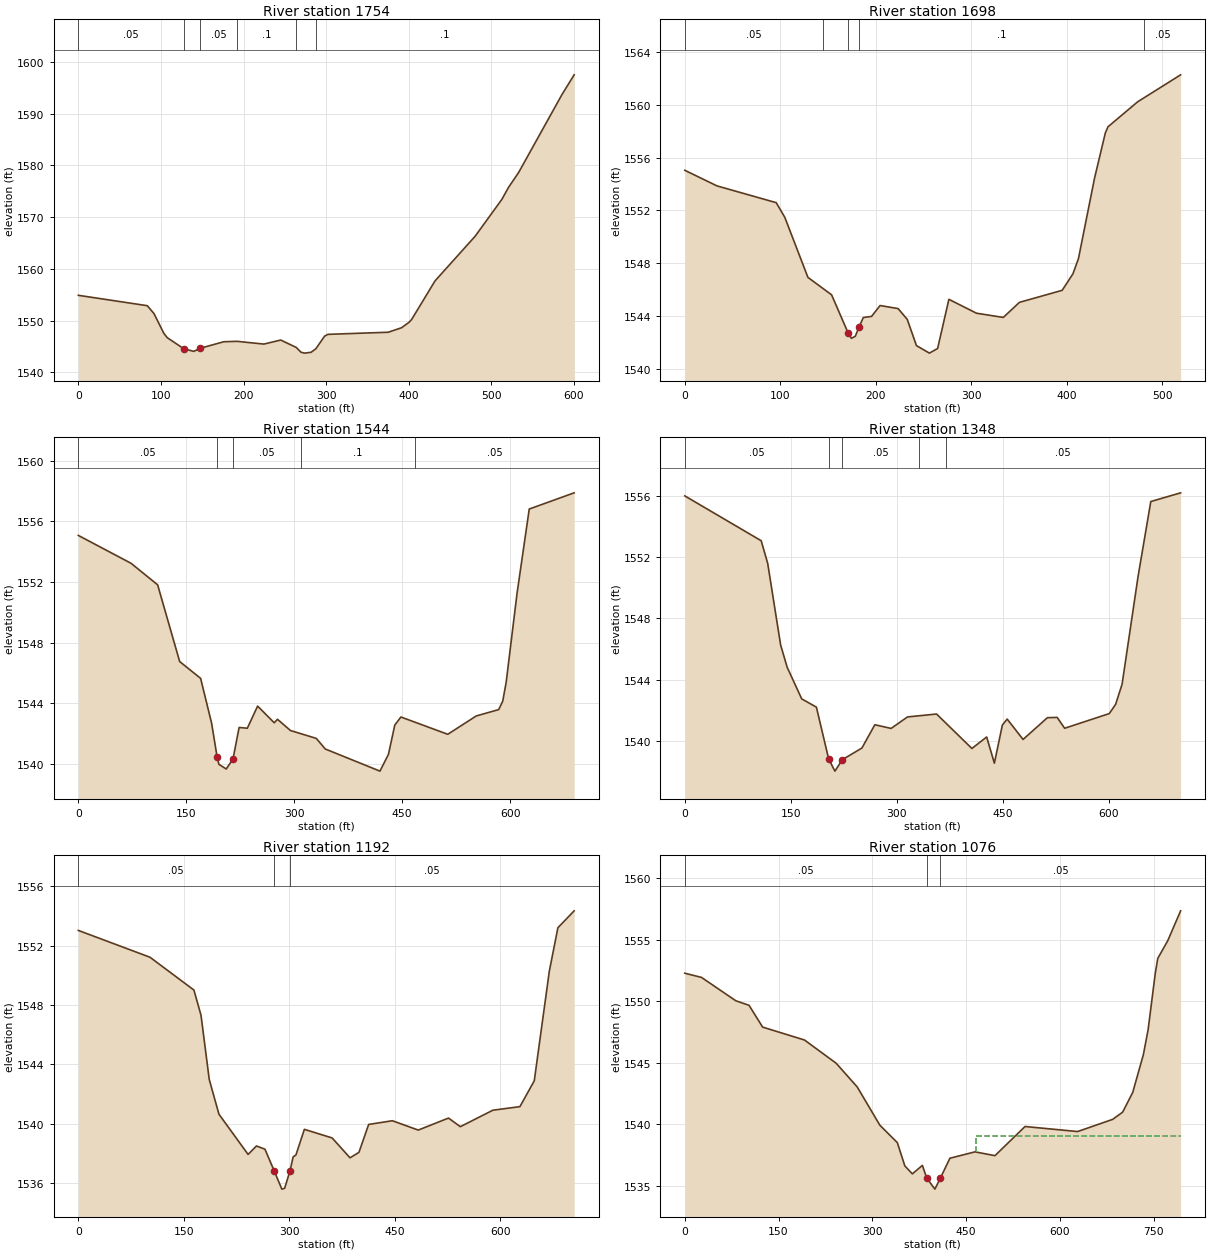
Type RM Length L Ch R = 1 ,1754    ,58.8,55.9,57.3
XS GIS Cut Line= 4
2476647.62036395601668.1833104342476843.80091956601687.280532643
2476972.27314177  601713.32219932477241.37036398601753.252754882
#Sta/Elev= 30
       0  1554.9    83.5 1552.89    91.6 1551.36   103.6 1547.53   107.6 1546.71
  127.671544.563   139.8 1544.06   147.4 1544.65     176 1545.92   192.1    1546
   224.6 1545.47     245 1546.25   263.8 1544.82   269.5  1543.9   273.6 1543.72
   281.7 1543.88   287.5 1544.56   298.1    1547   302.1 1547.35   375.2 1547.76
   391.3 1548.63   400.5 1549.71   403.5 1550.23   431.8 1557.69   480.3 1566.31
   512.7 1573.45   520.8 1575.78   532.9 1578.62   585.5 1593.73   600.2 1597.53
#Mann= 6 ,-1 , 0
       0     .05       0  127.67    .045       0   147.4     .05       0
   192.1      .1       0   263.8    .045       0   287.5      .1       0
Bank Sta=127.67,147.4
XS Rating Curve= 0 ,0
Exp/Cntr(USF)=0,0
Exp/Cntr=0.3,0.1

Type RM Length L Ch R = 1 ,1698    ,145.6,153.7,157.4
XS GIS Cut Line= 4
2476630.25925288601690.7527548822476816.02314174601741.099977091
2476864.63425285601814.0166437632477034.77314174601982.419421539
#Sta/Elev= 30
       0 1555.04    33.7 1553.86    95.8 1552.59   104.8 1551.48     129 1546.94
   153.8 1545.62     171 1542.76   174.6 1542.33   178.7 1542.49   182.4 1543.16
     187  1543.9   195.7 1543.99   204.6 1544.81   223.5 1544.58   233.1 1543.76
   242.7 1541.78   256.3 1541.21   264.9 1541.56   276.7 1545.28   305.6 1544.23
   333.7 1543.91   350.6 1545.05   395.4 1545.96   406.7 1547.21   412.5 1548.37
   429.3 1554.44   440.6 1557.86   443.4 1558.33   474.5 1560.22   519.5 1562.26
#Mann= 5 ,-1 , 0
       0     .05       0  144.47      .1       0     171    .045       0
   182.4      .1       0  481.58     .05       0
Bank Sta=171,182.4
XS Rating Curve= 0 ,0
Exp/Cntr(USF)=0,0
Exp/Cntr=0.3,0.1

Type RM Length L Ch R = 1 ,1544    ,200.8,196.9,193.3
XS GIS Cut Line= 4
2476611.16203064601708.1138659722476682.34258619601791.447199315
2476859.42591953602017.1416437482477057.34258619602232.419421524
#Sta/Elev= 30
       0 1555.08    73.3 1553.24   110.2 1551.82   140.8 1546.76   169.9 1545.65
   185.2 1542.69  192.821540.464   195.3 1539.98   205.5 1539.67   214.9 1540.33
   223.4 1542.41   234.8 1542.36   249.1 1543.82   272.2 1542.72   276.7 1542.95
   294.7 1542.21   330.6 1541.69   343.1 1540.99   419.1 1539.53   430.9 1540.64
   439.7 1542.57   448.2  1543.1   513.3 1541.96   552.9 1543.17   584.1 1543.59
   589.7 1544.15   594.5 1545.41   609.5 1551.24   626.5 1556.82   688.9 1557.89
#Mann= 5 ,-1 , 0
       0     .05       0  192.82    .045       0   214.9     .05       0
  308.79      .1       0  468.21     .05       0
Bank Sta=192.82,214.9
XS Rating Curve= 0 ,0
Exp/Cntr(USF)=0,0
Exp/Cntr=0.3,0.1

Type RM Length L Ch R = 1 ,1348    ,158.4,155.5,148.4
XS GIS Cut Line= 4
2476434.07869732  601916.44719932476531.30091956601965.058310419
2476767.41203067602098.7388659722477052.13425285602248.044421524
#Sta/Elev= 30
       0    1556   108.1 1553.07   117.3 1551.59   135.6 1546.26   144.8 1544.81
   165.4 1542.74   186.2  1542.2  203.521538.819   212.4 1538.02     223 1538.77
   250.6 1539.53   268.9 1541.05   291.9 1540.81   315.1 1541.56   356.2 1541.75
   406.2  1539.5   427.1 1540.25     438 1538.54   449.3 1541.03   456.1 1541.42
   478.6 1540.09     513 1541.51   526.8 1541.53   537.4 1540.82   600.6 1541.78
   609.6 1542.39   618.7  1543.7   641.2 1550.71   659.3 1555.63   701.5  1556.2
#Mann= 5 ,-1 , 0
       0     .05       0  203.52    .045       0     223     .05       0
  331.55      .1       0  368.95     .05       0
Bank Sta=203.52,223
XS Rating Curve= 0 ,0
Exp/Cntr(USF)=0,0
Exp/Cntr=0.3,0.1

Type RM Length L Ch R = 1 ,1192    ,114.7,115.6,114.5
XS GIS Cut Line= 4
2476375.05091956602091.7944215392476583.38425288602168.183310419
2476704.91203067602162.9749771062477048.66203064 602274.08608821
#Sta/Elev= 30
       0 1553.03   101.9 1551.22   164.3 1549.01   174.4 1547.31   186.1 1542.98
   199.9 1540.64   241.3 1537.93   253.2  1538.5   265.3 1538.28  278.371536.825
   289.3 1535.59   293.3 1535.65  300.931536.824   305.3 1537.76   309.3 1537.89
   321.3 1539.62   360.8 1539.04   386.2  1537.7   398.9 1538.07   412.7 1539.95
   446.4  1540.2   483.2 1539.57   526.2 1540.38     543  1539.8   589.3 1540.91
   627.7 1541.15   648.1 1542.89   669.5 1550.28   681.7 1553.21   704.8 1554.35
#Mann= 3 ,-1 , 0
       0     .05       0  278.37    .045       0  300.93     .05       0
Bank Sta=278.37,300.93
XS Rating Curve= 0 ,0
Exp/Cntr(USF)=0,0
Exp/Cntr=0.3,0.1

Type RM Length L Ch R = 1 ,1076    ,244.1,258.3,273.4
XS GIS Cut Line= 4
2476293.45369732602194.2249770912476553.87036395602282.766643748
2476734.42591953 602274.086088212477071.23147509602293.183310419
#Sta/Elev= 30
       0 1552.28    26.7 1551.94    81.6 1550.04   102.8 1549.67   124.5  1547.9
   191.5 1546.85   242.2 1544.96   275.9 1543.03     312 1539.93     340 1538.51
     352 1536.62     364 1535.97   380.1 1536.66  386.981535.632   400.1 1534.73
  408.921535.631   424.1 1537.24   464.2 1537.76   496.2 1537.45   544.3 1539.82
   628.4 1539.41   684.5  1540.4   700.5 1540.99   716.6 1542.59   733.7 1545.68
   741.2 1547.69   752.6 1552.25   756.6 1553.48   772.6 1554.92   793.2 1557.35
#Mann= 3 ,-1 , 0
       0     .05       0  386.98    .045       0  408.92     .05       0
#XS Ineff= 1 ,-1
  466.39793.1678 1539.08
Permanent Ineff=
       F
Bank Sta=386.98,408.92
XS Rating Curve= 0 ,0
Exp/Cntr(USF)=0,0
Exp/Cntr=0.3,0.1