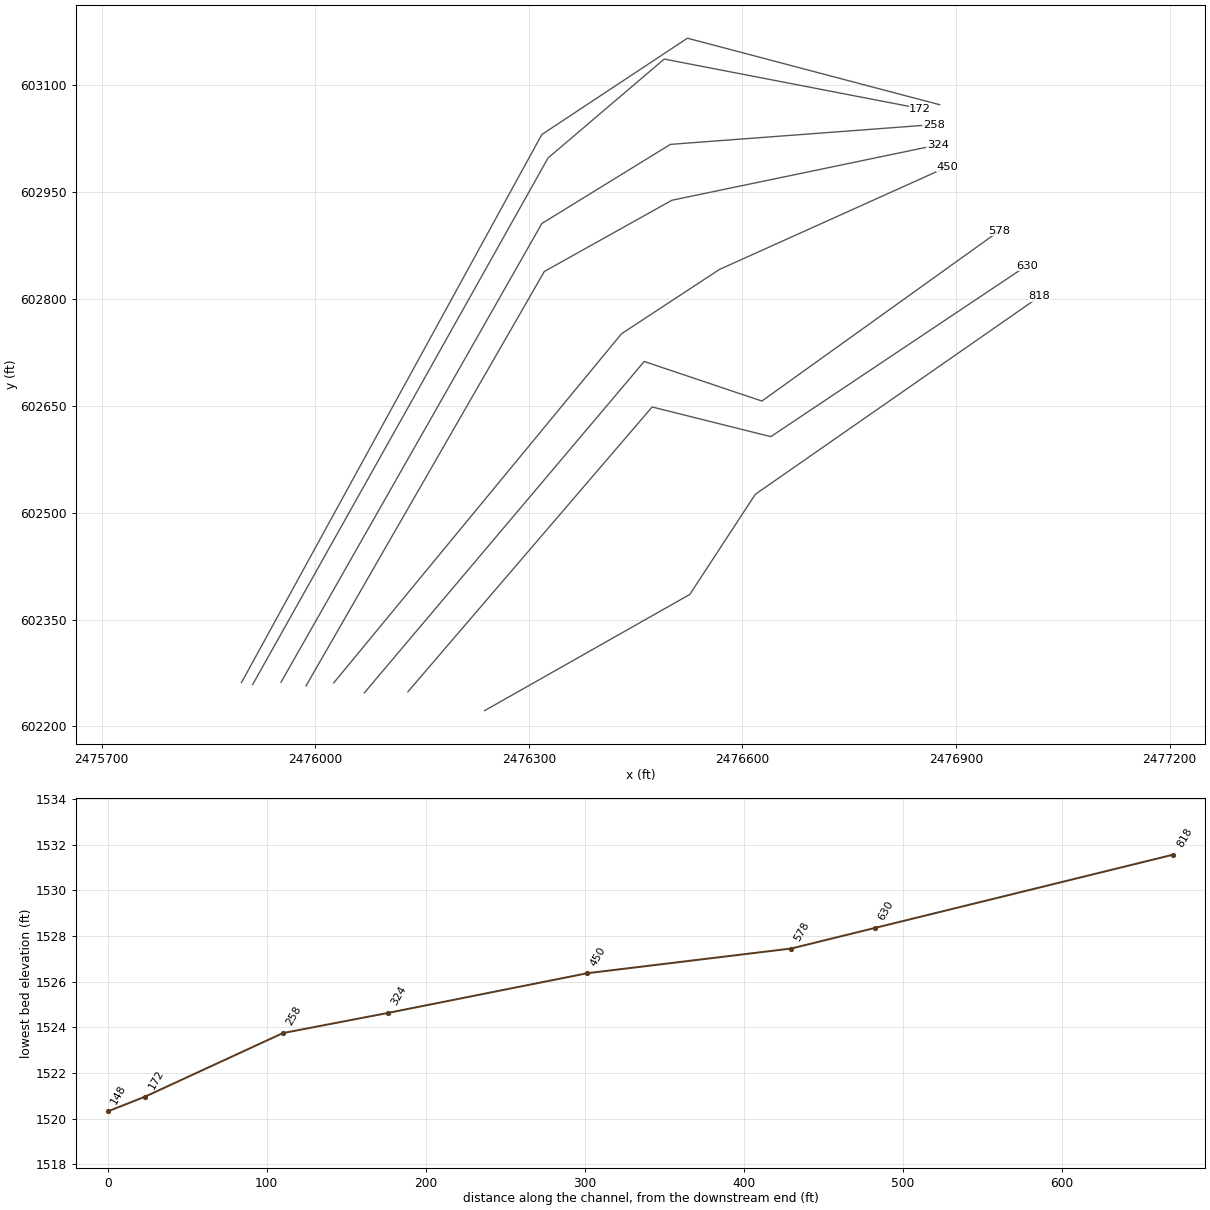
HEC-RAS study DETIMERRN.prj: DETIMERRN

--- DETIMERRN.g01 (geometry) --- (continued)

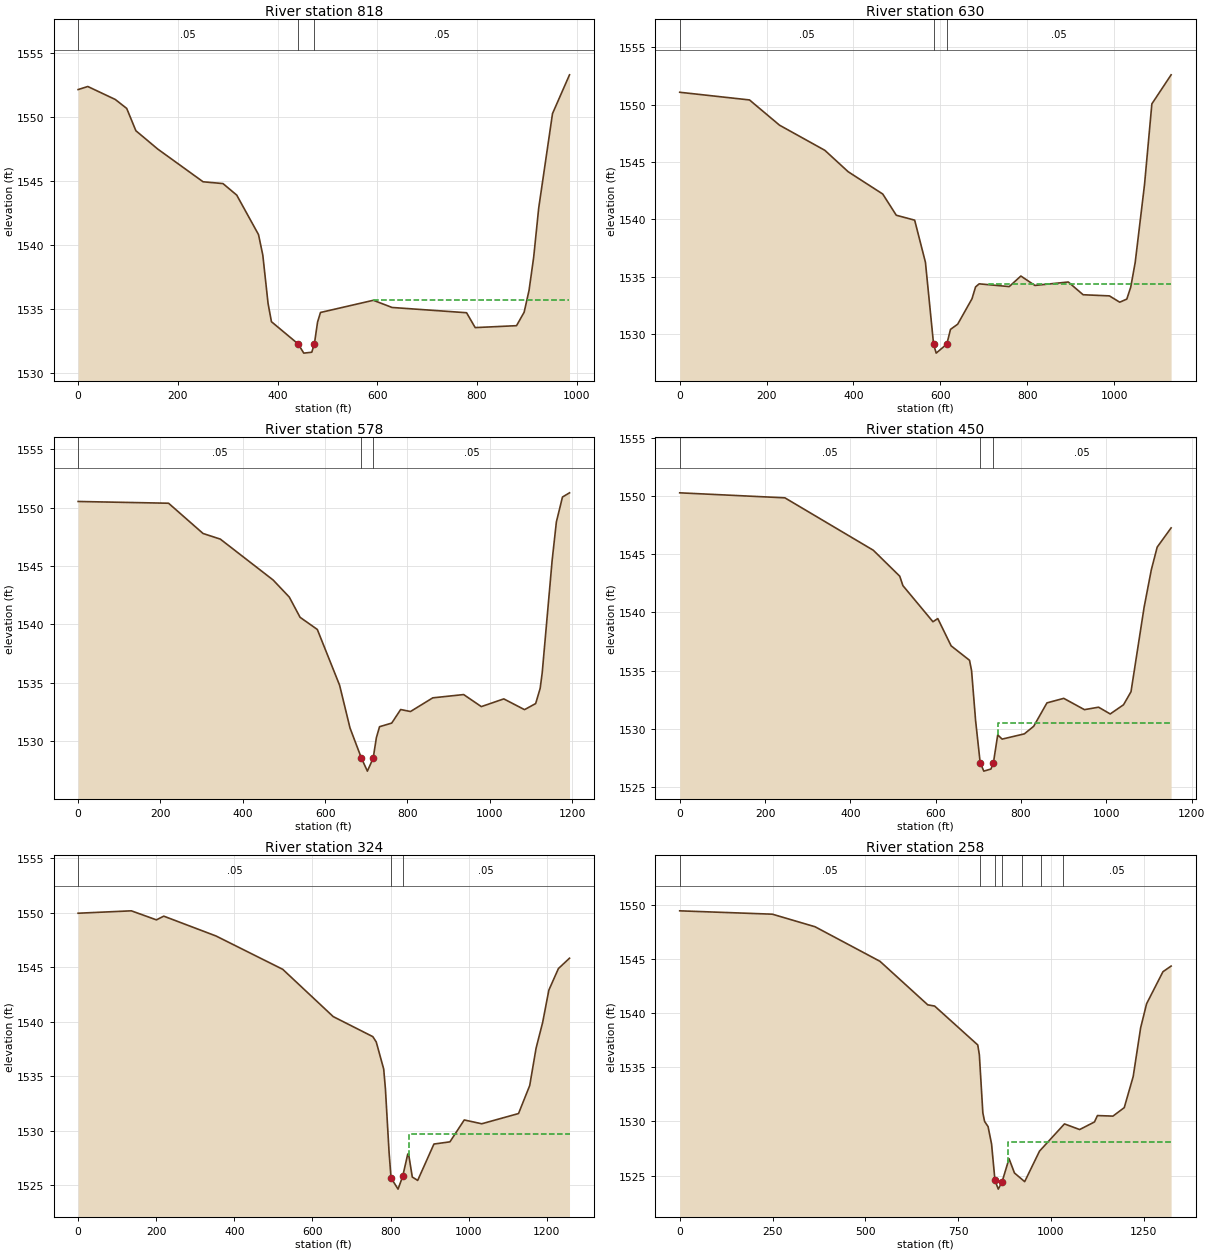
Type RM Length L Ch R = 1 ,818     ,201,187.7,159.8
XS GIS Cut Line= 4
2476237.89814177602222.0027548822476526.09258622602385.197199315
2476618.10647509  602525.82219932477017.41203067602803.599977106
#Sta/Elev= 30
       0 1552.11    19.4 1552.35    74.5 1551.34    97.5 1550.64   115.9  1548.9
   159.8 1547.47   250.7 1544.92   290.6 1544.78   318.2 1543.88   361.9  1540.8
   370.5  1539.2     381 1535.44   387.8 1534.01  441.311532.277   452.7 1531.56
   468.7 1531.63  473.931532.278   480.3 1533.98   486.2 1534.73   592.2 1535.68
   629.8 1535.12   779.2 1534.71   796.5 1533.55   879.4  1533.7   894.7 1534.75
   904.5 1536.45   913.8 1539.03   923.9 1542.87   951.6 1550.24   985.7 1553.26
#Mann= 3 ,-1 , 0
       0     .05       0  441.31    .045       0  473.93     .05       0
#XS Ineff= 1 ,-1
  593.96985.6669 1535.67
Permanent Ineff=
       F
Bank Sta=441.31,473.93
XS Rating Curve= 0 ,0
Exp/Cntr(USF)=0,0
Exp/Cntr=0.3,0.1

Type RM Length L Ch R = 1 ,630     ,53.8,52.6,51.4
XS GIS Cut Line= 4
2476130.14351213602248.4495141362476473.19906768602648.449514136
2476639.86573437602606.7828474492476999.58795658602847.060625225
#Sta/Elev= 30
       0 1551.09   160.7 1550.42   229.8 1548.22   334.1 1546.03   387.9 1544.16
   467.4 1542.22   498.6 1540.37   540.9 1539.94   565.7 1536.27  584.421529.138
   590.4 1528.35  614.961529.138   623.4 1530.42   639.9 1530.87   672.9 1533.09
   681.1 1534.12   689.4 1534.39   758.6 1534.15   785.4 1535.07   817.7 1534.25
   894.6 1534.55   928.7 1533.44   989.3 1533.34    1013 1532.79  1029.3 1533.06
  1038.3  1534.1  1048.6 1536.25  1070.1 1543.05    1087 1550.08  1131.3 1552.61
#Mann= 3 ,-1 , 0
       0     .05       0  584.42    .045       0  614.96     .05       0
#XS Ineff= 2 , 0
                          711.11         1534.41
Permanent Ineff=
       F       F
Bank Sta=584.42,614.96
XS Rating Curve= 0 ,0
Exp/Cntr(USF)=0,0
Exp/Cntr=0.3,0.1

Type RM Length L Ch R = 1 ,578     ,115.1,128.1,139.8
XS GIS Cut Line= 4
  2476069.032401 602247.060625242476462.08795655602712.338403016
2476627.36573434602656.7828474492476960.69906768602895.671736345
#Sta/Elev= 30
       0 1550.52   219.7 1550.37   303.5 1547.78   345.4  1547.3   473.7  1543.8
   512.9 1542.34   539.1 1540.61     581 1539.57   635.1  1534.8   660.4 1531.14
  688.071528.564   702.6 1527.45  716.691528.563   724.4 1530.31   732.1 1531.25
   761.7 1531.56   783.4 1532.72   807.3 1532.55   861.4 1533.72   936.4    1534
   979.3 1532.97  1033.9 1533.63  1084.2 1532.71  1111.3 1533.23  1122.2 1534.53
  1127.2 1535.87  1151.4 1545.51  1161.6 1548.77  1176.4  1550.9  1193.5 1551.26
#Mann= 3 ,-1 , 0
       0     .05       0  688.07    .045       0  716.69     .05       0
Bank Sta=688.07,716.69
XS Rating Curve= 0 ,0
Exp/Cntr(USF)=0,0
Exp/Cntr=0.3,0.1

Type RM Length L Ch R = 1 ,450     ,125.9,125.5,123.5
XS GIS Cut Line= 4
2476025.97684547602260.949514136 2476430.1435121602751.227291897
2476567.64351213602841.5050696882476888.47684544602985.949514136
#Sta/Elev= 30
       0 1550.27   246.5 1549.84   453.7 1545.34   515.7 1543.11   523.1  1542.3
   593.5  1539.2   604.9 1539.47   636.1 1537.13   679.2 1535.89     684 1535.01
   693.5  1530.7   704.21527.095   712.7 1526.37   729.5 1526.55  735.261527.095
   745.3 1529.48   755.7 1529.12   807.7 1529.57   829.6 1530.22   860.7 1532.23
   900.1 1532.62   948.5 1531.65   981.7 1531.86    1009 1531.28  1040.2 1532.07
  1057.7 1533.19  1088.4 1540.44  1105.3 1543.66  1119.1 1545.61  1151.7 1547.26
#Mann= 3 ,-1 , 0
       0     .05       0   704.2    .045       0  735.26     .05       0
#XS Ineff= 2 , 0
                          745.68         1530.54
Permanent Ineff=
       F       F
Bank Sta=704.2,735.26
XS Rating Curve= 0 ,0
Exp/Cntr(USF)=0,0
Exp/Cntr=0.3,0.1

Type RM Length L Ch R = 1 ,324     ,65.8,65.9,66.3
XS GIS Cut Line= 4
2475987.08795658602256.7828474492476321.81017882602838.727291912
2476500.97684544602938.7272919122476874.58795655603016.505069673
#Sta/Elev= 30
       0 1549.96   136.3 1550.18   200.5 1549.35   219.3 1549.69   353.1 1547.87
   523.9 1544.81   653.1 1540.47   754.5 1538.63   763.3 1538.14   782.4 1535.65
   786.8 1533.83   796.1 1528.03  801.181525.662   819.1 1524.63   830.9 1525.79
     844 1527.85   846.5 1527.76   855.6 1525.74   869.4 1525.43     911 1528.77
   951.9 1528.97   988.6 1530.98  1033.4 1530.63  1127.6 1531.57  1156.2 1534.14
  1172.5 1537.57  1189.3 1539.93  1205.2  1542.9  1229.7 1544.88  1258.1 1545.83
#Mann= 3 ,-1 , 0
       0     .05       0  801.18    .045       0   830.9     .05       0
#XS Ineff= 2 , 0
                          846.91         1529.69
Permanent Ineff=
       F       F
Bank Sta=801.18,830.9
XS Rating Curve= 0 ,0
Exp/Cntr(USF)=0,0
Exp/Cntr=0.5,0.3

Type RM Length L Ch R = 1 ,258     ,84.9,86.6,88
XS GIS Cut Line= 4
 2475952.0185121602261.9911807922476318.33795655602906.088403016
2476498.89351213603017.1995141212476868.68517879603044.977291912
#Sta/Elev= 30
       0 1549.44   249.5 1549.13   364.6 1547.97   539.5 1544.78   668.3 1540.76
   686.7 1540.65   802.9 1537.06   807.2 1536.16   816.6  1530.8   821.3    1530
   830.7 1529.52   840.1 1527.92  849.281524.554   858.2 1523.75   868.3 1524.41
   887.2 1526.56   901.8 1525.24   929.3 1524.44   969.3 1527.26  1036.5 1529.77
  1077.5 1529.25  1117.3 1529.95  1125.3 1530.54  1167.1 1530.49  1197.5 1531.27
  1221.6 1534.14  1241.7 1538.64  1257.7 1540.86  1301.8 1543.82  1323.8 1544.34
#Mann= 7 ,-1 , 0
       0     .05       0  809.59     .06       0  849.28    .045       0
   868.3     .06       0  922.56     .05       0  972.95     .06       0
 1031.44     .05       0
#XS Ineff= 2 , 0
                           883.4         1528.08
Permanent Ineff=
       F       F
Bank Sta=849.28,868.3
XS Rating Curve= 0 ,0
Exp/Cntr(USF)=0,0
Exp/Cntr=0.5,0.3

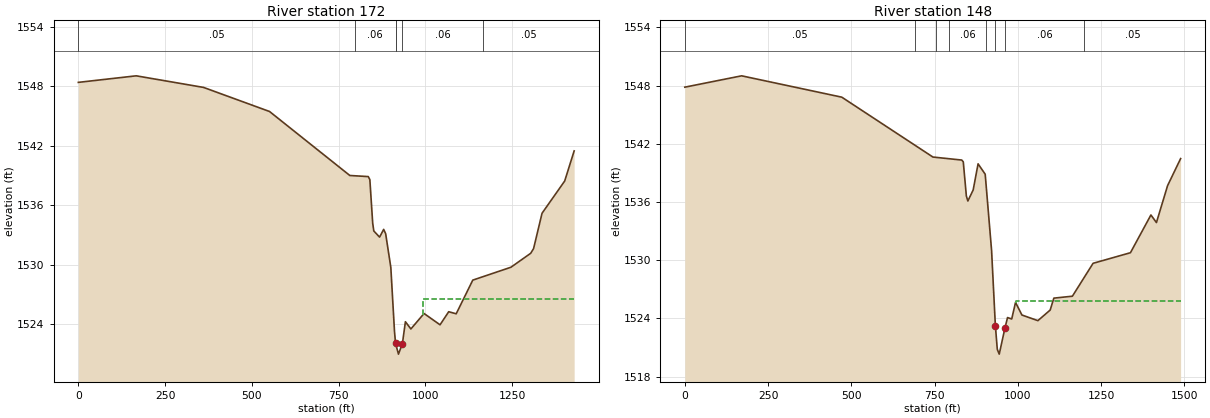
Type RM Length L Ch R = 1 ,172     ,24.4,23.6,24.1
XS GIS Cut Line= 4
2475912.08795658602258.5189585832476327.01851213602998.102291912
2476490.21295658603136.9911807922476849.58795655603067.546736345
#Sta/Elev= 30
       0  1548.4   166.8 1549.06   360.7 1547.89   550.8 1545.46   782.1    1539
   835.2 1538.89   839.8 1538.58     848 1534.17   851.2  1533.4   867.8 1532.78
   879.6 1533.56   885.3 1533.13   900.2 1529.72   910.8 1523.24  913.861522.043
   922.2 1520.97  933.581522.042   942.2 1524.24     958 1523.51   995.9 1525.07
    1042 1523.93  1066.9 1525.25  1088.5 1525.04  1136.3 1528.44  1246.2 1529.74
  1303.2 1531.15  1311.4 1531.62  1335.8 1535.19    1401 1538.44  1428.3 1541.48
#Mann= 6 ,-1 , 0
       0     .05       0  797.05     .06       0  913.76      .1       0
  913.86    .045       0  933.58     .06       0  1166.4     .05       0
#XS Ineff= 2 , 0
                          992.04         1526.53
Permanent Ineff=
       F       F
Bank Sta=913.86,933.58
XS Rating Curve= 0 ,0
Exp/Cntr(USF)=0,0
Exp/Cntr=0.5,0.3

Type RM Length L Ch R = 1 ,148     ,,,
XS GIS Cut Line= 4
2475896.45494279602261.4045273672476318.30179158603031.033511043
2476522.78480608603166.2821190532476877.00735086603072.896175427
#Sta/Elev= 30
       0 1547.83   170.7    1549   471.5  1546.8   745.2 1540.63   831.9 1540.32
   836.4 1540.13   845.6 1536.61   850.1  1536.1   866.1 1537.24   880.8 1539.93
   902.2 1538.86   921.4 1530.99   932.7 1523.27   938.5 1520.82   944.3 1520.32
   961.6 1523.02   969.3 1524.09   981.8 1523.94   993.3 1525.65  1012.5 1524.35
  1060.4 1523.77  1097.3 1524.86  1108.4 1526.09  1164.1 1526.29  1226.2 1529.68
  1338.4 1530.77  1399.9 1534.66  1416.5 1533.88  1449.9 1537.68  1489.1 1540.47
#Mann= 8 ,-1 , 0
       0     .05       0  689.96     .06       0  754.41     .05       0
  793.68     .06       0  905.25      .1       0   932.7    .045       0
   961.6     .06       0 1199.75     .05       0
#XS Ineff= 2 , 0
                          994.24         1525.76
Permanent Ineff=
       F       F
Bank Sta=932.7,961.6
XS Rating Curve= 0 ,0
Exp/Cntr(USF)=0,0
Exp/Cntr=0.3,0.1
LCMann Table=0

Chan Stop Cuts=-1
Use User Specified Reach Order=0
Composite Channel Slope=5